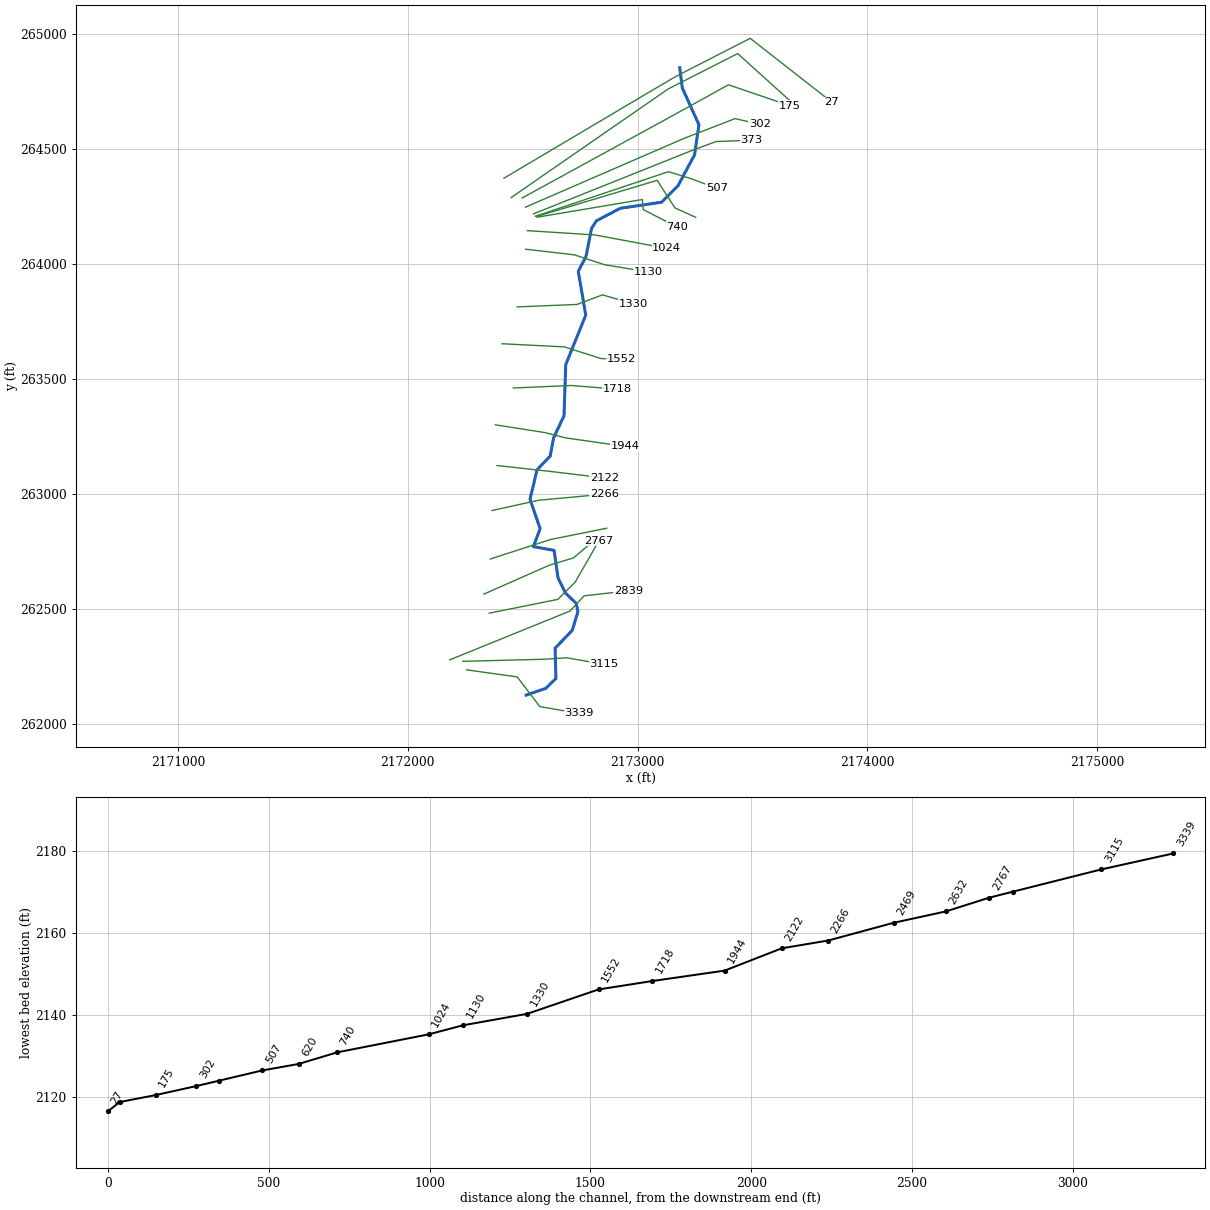
--- BROADRN.prj (project) ---

Proj Title=BROADRN
Current Plan=p01
Default Exp/Contr=0,0
English Units
Geom File=g01
Flow File=f01
Plan File=p01
Background Map Layer=DPs_HMS_shifted
Background Map Layer=QC_TUCKHORN
BEGIN DESCRIPTION:
Stream Name- Broad Run
Flood Zone: Zone A
Greenbrier County, WV
County-Wide Study
WVDHSEM-2018-3, Flood Risk Project
HEC-RAS Version: 5.0.7
General Notes:
For the Hydrology HECHMS 4.2.1 was used.
END DESCRIPTION:
DSS File=dss
DSS Export Rating Curves= 0
DSS Export Rating Curve Sorted= 0
DSS Export Volume Flow Curves= 0
DXF Filename=..\..\..\H1\MEADOWRV4\MEADOWRV4.
DXF OffsetX= 0
DXF OffsetY= 0
DXF ScaleX= 0
DXF ScaleY= 0

--- BROADRN.p01 (plan) ---

Plan Title=Floodplain
Program Version=5.07
Short Identifier=Floodplain
Geom File=g01
Flow File=f01
Subcritical Flow
K Sum by GR= 0
Std Step Tol= 0.01
Critical Tol= 0.01
Num of Std Step Trials= 20
Max Error Tol= 0.3
Flow Tol Ratio= 0.001
Split Flow NTrial= 30
Split Flow Tol= 0.02
Split Flow Ratio= 0.02
Log Output Level= 0
Friction Slope Method= 1
Unsteady Friction Slope Method= 2
Unsteady Bridges Friction Slope Method= 1
Parabolic Critical Depth
Global Vel Dist= 0 , 0 , 0
Global Log Level= 0
CheckData=True
Encroach Param=-1 ,0,0, 0
Computation Interval=0.1SEC
Output Interval=1MIN
Instantaneous Interval=Max Profile
Mapping Interval=1HOUR
Computation Time Step Use Courant=        0
Computation Time Step Use Time Series=    0
Computation Time Step Count To Double=0
Computation Time Step Max Doubling=0
Computation Time Step Max Halving=0
Computation Time Step Residence Courant=0
Run HTab= 0
Run UNet= 0
Run Sediment= 0
Run PostProcess= 0
Run WQNet= 0
Run RASMapper= 0
UNET Theta= 0
UNET Theta Warmup= 0
UNET ZTol= 0
UNET ZSATol= 0
UNET MxIter= 0
UNET Max Iter WO Improvement= 0
UNET MaxInSteps= 0
UNET DtIC= 0
UNET DtMin= 0
UNET MaxCRTS= 0
UNET WFStab= 0
UNET SFStab= 0
UNET WFX= 1
UNET SFX= 1
UNET 1D Methodology=Finite Difference
UNET DSS MLevel= 1
UNET Pardiso=0
UNET DZMax Abort= 0
UNET Use Existing IB Tables= 0
UNET Froude Reduction=False
UNET Froude Limit= 0
UNET Froude Power= 0
UNET D1 Cores= 0
UNET D2 Coriolis=0
UNET D2 Cores= 0
UNET D2 Theta= 1
UNET D2 Theta Warmup= 1
UNET D2 Z Tol= 0.01
UNET D2 Volume Tol= 0.01
UNET D2 Max Iterations= 20
UNET D2 Equation= 0
UNET D2 RampUpFraction=0.1
UNET D2 TimeSlices= 1
UNET D2 BCVolumeCheck=0
UNET D1D2 MaxIter= 0
UNET D1D2 ZTol=0.01
UNET D1D2 QTol=0.1
UNET D1D2 MinQTol=1
DSS File=dss
Write IC File= 0
Write IC File at Fixed DateTime=0
Write IC File at Sim End=0
Echo Input=False
Echo Parameters=False
Echo Output=False
Write Detailed= 0
HDF Write Warmup=0
HDF Write Time Slices=0
HDF Flush=0
HDF Face Node Velocities=0
HDF Compression= 1
HDF Chunk Size= 1
HDF Spatial Parts= 1
HDF Use Max Rows=0
HDF Fixed Rows= 1
Calibration Method= 0
Calibration Iterations= 20
Calibration Max Change=0.05
Calibration Tolerance=0.2
Calibration Maximum=1.5
Calibration Minimum=0.5
Calibration Optimization Method= 1
WQ AD Non Conservative
WQ ULTIMATE=-1
WQ Max Comp Step=1HOUR
WQ Output Interval=15MIN
WQ Output Selected Increments= 0
WQ Output face flow=0
WQ Output face velocity=0
WQ Output face area=0
WQ Output face dispersion=0
WQ Output cell volume=0
WQ Output cell surface area=0
WQ Output cell continuity=0
WQ Output cumulative cell continuity=0
WQ Output face conc=0
WQ Output face dconc_dx=0
WQ Output face courant=0
WQ Output face peclet=0
WQ Output face adv mass=0
WQ Output face disp mass=0
WQ Output cell mass=0
WQ Output cell source sink temp=0
WQ Output nsm pathways=0
WQ Output nsm derived pathways=0
WQ Output MaxMinRange=-1
WQ Daily Max Min Mean=-1
WQ Daily Range=0
WQ Daily Time=0
WQ Create Restart=0
WQ Fixed Restart=0
WQ System Summary=0
WQ Write To DSS=0
WQ Use Fixed Temperature=0
Sorting and Armoring Iterations= 10
XS Update Threshold= 0.02
Bed Roughness Predictor= 0
Hydraulics Update Threshold= 0.02
Energy Slope Method= 1
Volume Change Method= 1
Sediment Retention Method= 0
XS Weighting Method= 0
Number of US Weighted Cross Sections= 1
Number of DS Weighted Cross Sections= 1
Upstream XS Weight=0
Main XS Weight=1
Downstream XS Weight=0
Number of DS XS's Weighted with US Boundary= 1
Upstream Boundary Weight= 1
Weight of XSs Associated with US Boundary= 0
Number of US XS's Weighted with DS Boundary= 1
Downstream Boundary Weight= 0.5
Weight of XSs Associated with DS Boundary= 0.5
Percentile Method= 0
Sediment Output Level= 3
Mass or Volume Output= 0
Output Increment Type= 1
Profile and TS Output Increment= 1
XS Output Flag= 0
XS Output Increment= 10
Write Gradation File= 0
Read Gradation Hotstart= 0
Write HDF5 File= 1
Write Binary Output= 1
Write DSS Sediment File= 0
SV Curve= 0
Specific Gage Flag= 0

--- BROADRN.f01 (steady flow) ---

Flow Title=MasterFlow
Program Version=5.07
Number of Profiles= 6
Profile Names=f1p,f10p,f4p,f2p,f02p,f1pplus
River Rch & RM=BROADRN,Main            ,3339
     761     339     488     619    1150     917
River Rch & RM=LAURELBR,Main            ,3440
     558     218     334     440     888     691
River Rch & RM=LAURELCK1,Main            ,8407
     526     277     369     445     736     778
River Rch & RM=LAURELCK1,Main            ,7622
     821     440     581     697    1140    1210
River Rch & RM=LAURELCK1,Main            ,6012
     949     512     674     807    1310    1400
River Rch & RM=LAURELCK1,Main            ,2069
    1180     639     838    1000    1620    1740
River Rch & RM=MLGNCK,Main            ,43088
    1400     765    1000    1190    1920    2070
River Rch & RM=MLGNCK,Main            ,41997
    1560     858    1120    1330    2140    2310
River Rch & RM=MLGNCK,Main            ,35646
    1910    1060    1370    1630    2610    2820
River Rch & RM=MLGNCK,Main            ,34400
    2210    1230    1600    1890    3010    3270
River Rch & RM=MLGNCK,Main            ,29681
    3770    2150    2750    3250    5090    5580
River Rch & RM=MLGNCK,Main            ,25204
    4210    2400    3080    3630    5670    6230
River Rch & RM=MLGNCK,Main            ,13347
    4770    2730    3490    4110    6400    7050
River Rch & RM=MLGNCKTR3,Main            ,13516
    1790     990    1290    1530    2450    2650
River Rch & RM=MLGNCKTR3,Main            ,9632
    2060    1140    1480    1760    2810    3040
River Rch & RM=MLGNCKTR4,Main            ,3322
     500     263     350     423     700     739
River Rch & RM=MLGNCKTR4,Main            ,2737
     557     294     391     471     778     823
River Rch & RM=TUCKHORN,Main            ,14873
     566     299     398     479     791     837
River Rch & RM=TUCKHORN,Main            ,12657
     639     339     450     542     891     945
River Rch & RM=TUCKHORN,Main            ,10275
    1150     622     817     976    1580    1700
River Rch & RM=TUCKHORN,Main            ,6291
    1390     758     991    1180    1900    2050
River Rch & RM=TUCKHORN,Main            ,4342
    1770     980    1280    1520    2430    2620
River Rch & RM=TUCKHORN,Main            ,346
    2140    1190    1540    1830    2910    3160
River Rch & RM=TUCKHORN,Main            ,239
    3116    1352    1964    2514    3780    4764
River Rch & RM=TUCKHORNT2,Main            ,1848
     570     301     400     482     796     842
Boundary for River Rch & Prof#=BROADRN,Main            , 1
Up Type= 0
Dn Type= 3
Dn Slope=0.05922
Boundary for River Rch & Prof#=BROADRN,Main            , 2
Up Type= 0
Dn Type= 3
Dn Slope=0.05922
Boundary for River Rch & Prof#=BROADRN,Main            , 3
Up Type= 0
Dn Type= 3
Dn Slope=0.05922
Boundary for River Rch & Prof#=BROADRN,Main            , 4
Up Type= 0
Dn Type= 3
Dn Slope=0.05922
Boundary for River Rch & Prof#=BROADRN,Main            , 5
Up Type= 0
Dn Type= 3
Dn Slope=0.05922
Boundary for River Rch & Prof#=BROADRN,Main            , 6
Up Type= 0
Dn Type= 3
Dn Slope=0.05922
Boundary for River Rch & Prof#=LAURELBR,Main            , 1
Up Type= 0
Dn Type= 3
Dn Slope=0.04145
Boundary for River Rch & Prof#=LAURELBR,Main            , 2
Up Type= 0
Dn Type= 3
Dn Slope=0.04145
Boundary for River Rch & Prof#=LAURELBR,Main            , 3
Up Type= 0
Dn Type= 3
Dn Slope=0.04145
Boundary for River Rch & Prof#=LAURELBR,Main            , 4
Up Type= 0
Dn Type= 3
Dn Slope=0.04145
Boundary for River Rch & Prof#=LAURELBR,Main            , 5
Up Type= 0
Dn Type= 3
Dn Slope=0.04145
Boundary for River Rch & Prof#=LAURELBR,Main            , 6
Up Type= 0
Dn Type= 3
Dn Slope=0.04145
Boundary for River Rch & Prof#=LAURELCK1,Main            , 1
Up Type= 0
Dn Type= 3
Dn Slope=0.009
Boundary for River Rch & Prof#=LAURELCK1,Main            , 2
Up Type= 0
Dn Type= 3
Dn Slope=0.009
Boundary for River Rch & Prof#=LAURELCK1,Main            , 3
Up Type= 0
Dn Type= 3
Dn Slope=0.009
Boundary for River Rch & Prof#=LAURELCK1,Main            , 4
Up Type= 0
Dn Type= 3
Dn Slope=0.009
Boundary for River Rch & Prof#=LAURELCK1,Main            , 5
Up Type= 0
Dn Type= 3
Dn Slope=0.009
Boundary for River Rch & Prof#=LAURELCK1,Main            , 6
Up Type= 0
Dn Type= 3
Dn Slope=0.009
Boundary for River Rch & Prof#=MLGNCK,Main            , 1
Up Type= 0
Dn Type= 3
Dn Slope=0.0302
Boundary for River Rch & Prof#=MLGNCK,Main            , 2
Up Type= 0
Dn Type= 3
Dn Slope=0.0302
Boundary for River Rch & Prof#=MLGNCK,Main            , 3
Up Type= 0
Dn Type= 3
Dn Slope=0.0302
Boundary for River Rch & Prof#=MLGNCK,Main            , 4
Up Type= 0
Dn Type= 3
Dn Slope=0.0302
Boundary for River Rch & Prof#=MLGNCK,Main            , 5
Up Type= 0
Dn Type= 3
Dn Slope=0.0302
Boundary for River Rch & Prof#=MLGNCK,Main            , 6
Up Type= 0
Dn Type= 3
Dn Slope=0.0302
Boundary for River Rch & Prof#=MLGNCKTR3,Main            , 1
Up Type= 0
Dn Type= 3
Dn Slope=0.00395
Boundary for River Rch & Prof#=MLGNCKTR3,Main            , 2
Up Type= 0
Dn Type= 3
Dn Slope=0.00395
Boundary for River Rch & Prof#=MLGNCKTR3,Main            , 3
Up Type= 0
Dn Type= 3
Dn Slope=0.00395
Boundary for River Rch & Prof#=MLGNCKTR3,Main            , 4
Up Type= 0
Dn Type= 3
Dn Slope=0.00395
Boundary for River Rch & Prof#=MLGNCKTR3,Main            , 5
Up Type= 0
Dn Type= 3
Dn Slope=0.00395
Boundary for River Rch & Prof#=MLGNCKTR3,Main            , 6
Up Type= 0
Dn Type= 3
Dn Slope=0.00395
Boundary for River Rch & Prof#=MLGNCKTR4,Main            , 1
Up Type= 0
Dn Type= 3
Dn Slope=0.01609
Boundary for River Rch & Prof#=MLGNCKTR4,Main            , 2
Up Type= 0
Dn Type= 3
Dn Slope=0.01609
Boundary for River Rch & Prof#=MLGNCKTR4,Main            , 3
Up Type= 0
Dn Type= 3
Dn Slope=0.01609
Boundary for River Rch & Prof#=MLGNCKTR4,Main            , 4
Up Type= 0
Dn Type= 3
Dn Slope=0.01609
Boundary for River Rch & Prof#=MLGNCKTR4,Main            , 5
Up Type= 0
Dn Type= 3
Dn Slope=0.01609
Boundary for River Rch & Prof#=MLGNCKTR4,Main            , 6
Up Type= 0
Dn Type= 3
Dn Slope=0.01609
Boundary for River Rch & Prof#=TUCKHORN,Main            , 1
Up Type= 0
Dn Type= 1
Dn Known WS=2122.5
Boundary for River Rch & Prof#=TUCKHORN,Main            , 2
Up Type= 0
Dn Type= 1
Dn Known WS=2120.48
Boundary for River Rch & Prof#=TUCKHORN,Main            , 3
Up Type= 0
Dn Type= 1
Dn Known WS=2121.09
Boundary for River Rch & Prof#=TUCKHORN,Main            , 4
Up Type= 0
Dn Type= 1
Dn Known WS=2121.64
Boundary for River Rch & Prof#=TUCKHORN,Main            , 5
Up Type= 0
Dn Type= 1
Dn Known WS=2123.27
Boundary for River Rch & Prof#=TUCKHORN,Main            , 6
Up Type= 0
Dn Type= 1
Dn Known WS=2124.99
Boundary for River Rch & Prof#=TUCKHORNT2,Main            , 1
Up Type= 0
Dn Type= 3
Dn Slope=0.02818
Boundary for River Rch & Prof#=TUCKHORNT2,Main            , 2
Up Type= 0
Dn Type= 3
Dn Slope=0.02818
Boundary for River Rch & Prof#=TUCKHORNT2,Main            , 3
Up Type= 0
Dn Type= 3
Dn Slope=0.02818
Boundary for River Rch & Prof#=TUCKHORNT2,Main            , 4
Up Type= 0
Dn Type= 3
Dn Slope=0.02818
Boundary for River Rch & Prof#=TUCKHORNT2,Main            , 5
Up Type= 0
Dn Type= 3
Dn Slope=0.02818
Boundary for River Rch & Prof#=TUCKHORNT2,Main            , 6
Up Type= 0
Dn Type= 3
Dn Slope=0.02818
DSS Import GetInterval= 0
DSS Import GetPeak= 0
DSS Import FillOption= 0

--- BROADRN.g01 (geometry) ---

Geom Title=MasterGeometry
Program Version=5.07

River Reach=BROADRN         ,Main
Reach XY= 30
     2172515.149      262124.111     2172599.774      262153.265
      2172644.42      262196.337     2172640.813      262328.418
     2172715.635      262405.995     2172740.057      262487.079
     2172732.478      262523.828     2172685.541      262568.419
     2172653.537       262634.42     2172636.462      262753.878
     2172546.302      262770.256     2172575.683       262848.45
     2172531.716       262976.17     2172562.256      263104.895
     2172619.449      263164.366     2172634.327      263243.718
     2172679.568      263339.727     2172687.133      263562.574
     2172774.174      263777.856     2172741.563      263968.631
     2172775.166      264032.548     2172799.647      264155.464
     2172820.588      264188.399      2172925.07      264242.913
     2173104.751      264269.381     2173175.798      264340.772
     2173247.744       264475.48      2173266.81      264606.413
     2173194.388      264766.7762173183.30412276264854.545083815

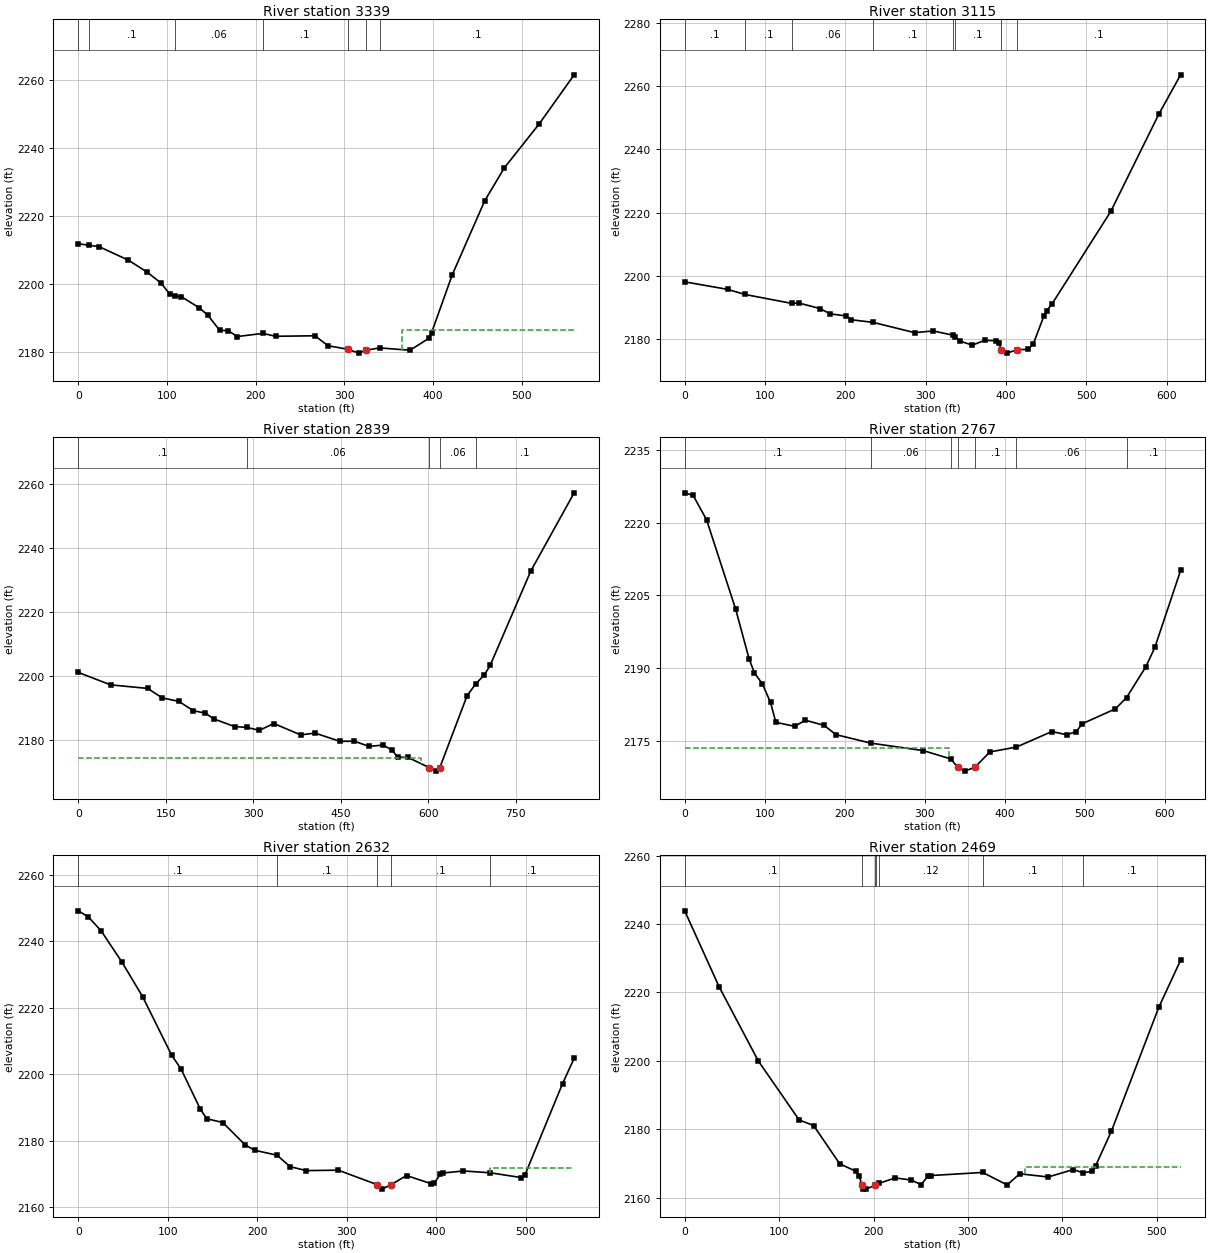
Type RM Length L Ch R = 1 ,3339    ,224,224,224
XS GIS Cut Line= 4
2172255.45386811262234.0495531682172475.81300494262203.230093471
2172574.43527597262073.7883627452172745.48327729262044.509876033
#Sta/Elev= 30
       0 2211.74   12.632211.279    23.5 2210.89    56.6 2206.89    77.1 2203.48
    93.1 2200.22     103 2196.96  108.762196.435   116.2 2196.13   136.1 2192.94
   146.1 2190.69   159.3 2186.28   169.3  2186.1   179.2 2184.41  208.112185.344
   222.3 2184.49   266.6 2184.64   281.6  2181.7  303.412180.683   316.1 2179.53
   324.6 2180.41  339.572181.071   373.8 2180.38   394.8 2183.85   398.1 2185.51
   421.4 2202.59     458 2224.38   480.1 2234.09   519.1 2246.93558.7711 2261.48
#Mann= 7 ,-1 , 0
       0      .1       0   12.63      .1       0  108.76     .06       0
  208.11      .1       0  303.41    .045       0   324.6      .1       0
  339.57      .1       0
#XS Ineff= 2 , 0
                          364.47          2186.3
Permanent Ineff=
       F       F
Bank Sta=303.41,324.6
XS Rating Curve= 0 ,0
Exp/Cntr(USF)=0,0
Exp/Cntr=0.3,0.1

Type RM Length L Ch R = 1 ,3115    ,276.3,276.3,276.3
XS GIS Cut Line= 4
2172238.50316527262271.0329048042172599.09084373262280.278742713
2172690.00824983262286.4426346532172853.35138622262258.705120926
#Sta/Elev= 30
       0 2198.13    53.4 2195.76   75.052194.147  133.712191.308     142 2191.46
   168.2 2189.71   181.4 2188.01     201 2187.37   207.6 2186.16  234.792185.321
   286.4 2182.08   309.3 2182.63  333.882181.297  336.152180.845   342.2 2179.47
   358.1 2178.14   373.6 2179.65   388.2 2179.53   391.5 2178.67  393.992176.716
   401.3 2175.62   414.32176.718   427.6 2176.79   434.2 2178.59   447.2  2187.3
   450.6 2188.98   457.3 2191.12   530.5 2220.35   590.3 2251.05617.5138 2263.51
#Mann= 8 ,-1 , 0
       0      .1       0   75.05      .1       0  133.71     .06       0
  234.79      .1       0  333.88     .06       0  336.15      .1       0
  393.99    .045       0   414.3      .1       0
#XS Ineff= 2 , 0
          376.87 2179.12
Permanent Ineff=
       F       F
Bank Sta=393.99,414.3
XS Rating Curve= 0 ,0
Exp/Cntr(USF)=0,0
Exp/Cntr=0.5,0.3

Type RM Length L Ch R = 1 ,2839    ,72.1,72.1,72.1
XS GIS Cut Line= 4
2172181.48716483262277.1967967442172705.41797968262489.851068652
2172767.05689907   262556.1129072172959.67852218262577.686528787
#Sta/Elev= 30
       0 2201.07    55.4 2197.17   119.1 2196.04   143.9 2193.09   172.2    2192
   197.5 2189.05   217.6 2188.33   232.4  2186.5   267.8 2184.11  289.392183.823
   310.3 2182.92   335.1 2185.06   381.1  2181.5   405.9 2182.06   448.4 2179.47
   473.2 2179.52     498 2177.91   522.7 2178.29   537.5 2176.75   547.5 2174.53
     565 2174.45  601.442171.254   613.3 2170.15  619.622171.254   666.4 2193.81
  680.952197.417   696.1 2200.35   705.8 2203.23   775.3 2232.75849.7672 2257.29
#Mann= 5 ,-1 , 0
       0      .1       0  289.39     .06       0  601.44    .045       0
  619.62     .06       0  680.95      .1       0
#XS Ineff= 2 , 0
          586.82 2174.16
Permanent Ineff=
       F       F
Bank Sta=601.44,619.62
XS Rating Curve= 0 ,0
Exp/Cntr(USF)=0,0
Exp/Cntr=0.5,0.3

Type RM Length L Ch R = 1 ,2767    ,134.9,134.9,134.9
XS GIS Cut Line= 4
2172354.07613914262480.6052307422172653.02489819262540.703177151
2172728.53257445262616.2108534082172831.77776444262796.504692635
#Sta/Elev= 30
       0  2226.2    10.6 2225.66    27.3 2220.65    63.7 2202.15    80.4 2191.93
    87.1    2189      97 2186.76   107.2  2182.9   113.9 2178.79   137.3 2177.97
   150.7 2179.22   174.1 2178.17   188.9 2176.25  232.28  2174.5   297.9 2172.95
  332.332171.234  340.96 2169.51   349.8 2168.71  362.57 2169.51   381.2 2172.67
  414.422173.683   458.7 2176.89     477 2176.23     489 2176.85   496.6  2178.5
   538.1 2181.58  551.912183.902     576 2190.25   587.3 2194.27619.4766 2210.17
#Mann= 7 ,-1 , 0
       0      .1       0  232.28     .06       0  332.33      .1       0
  340.96    .045       0  362.57      .1       0  414.42     .06       0
  551.91      .1       0
#XS Ineff= 2 , 0
          330.51 2173.45
Permanent Ineff=
       F       F
Bank Sta=340.96,362.57
XS Rating Curve= 0 ,0
Exp/Cntr(USF)=0,0
Exp/Cntr=0.5,0.3

Type RM Length L Ch R = 1 ,2632    ,162.6,162.6,162.6
XS GIS Cut Line= 4
2172330.96154436262563.8177719242172617.58251954262690.177556681
2172720.82770953262720.9970163772172822.53192653262807.291503528
#Sta/Elev= 30
       0  2249.2      11 2247.45    25.4 2243.25    48.5 2233.92      72 2223.34
   104.3 2205.78     115 2201.51   136.5 2189.44   143.7 2186.56   161.6 2185.42
   186.7 2178.65   197.5 2177.04   222.22175.573   236.9 2172.12   254.8 2170.93
   290.7 2171.06  333.692166.744   339.6 2165.35  350.022166.743     367 2169.45
   394.4    2167   397.9 2167.11   404.7  2169.8   408.1 2170.22   430.6 2170.82
  460.02 2170.29   495.2 2168.84   499.5 2169.71   541.4 2197.15554.3665 2204.75
#Mann= 5 ,-1 , 0
       0      .1       0   222.2      .1       0  333.69    .045       0
  350.02      .1       0  460.02      .1       0
#XS Ineff= 2 , 0
                          460.78         2171.71
Permanent Ineff=
       F       F
Bank Sta=333.69,350.02
XS Rating Curve= 0 ,0
Exp/Cntr(USF)=0,0
Exp/Cntr=0.3,0.1

Type RM Length L Ch R = 1 ,2469    ,203.3,203.3,203.3
XS GIS Cut Line= 3
2172358.69905809262716.3740974232172620.66446551262801.127611589
 2172865.6791701262850.438747104
#Sta/Elev= 30
       0 2243.85    36.6  2221.6      78 2199.99   121.2 2182.78   136.6 2181.12
   164.2 2169.95   181.5 2167.75   184.9 2166.49  187.522163.683   188.4 2162.73
   191.8 2162.56  201.822163.678  202.39 2163.76  206.092164.257   222.8 2165.84
   240.1 2165.21   250.4 2163.86   257.3 2166.26   260.8 2166.53  315.622167.432
   341.5 2163.79   354.9 2167.04     385 2166.11   411.8 2168.29  421.73  2167.3
   431.9 2167.81   435.2 2169.33     452 2179.52   502.1 2215.64 525.262 2229.44
#Mann= 7 ,-1 , 0
       0      .1       0  187.52    .045       0  201.82      .1       0
  202.39      .1       0  206.09     .12       0  315.62      .1       0
  421.73      .1       0
#XS Ineff= 2 , 0
                          360.31          2168.9
Permanent Ineff=
       F       F
Bank Sta=187.52,201.82
XS Rating Curve= 0 ,0
Exp/Cntr(USF)=0,0
Exp/Cntr=0.3,0.1

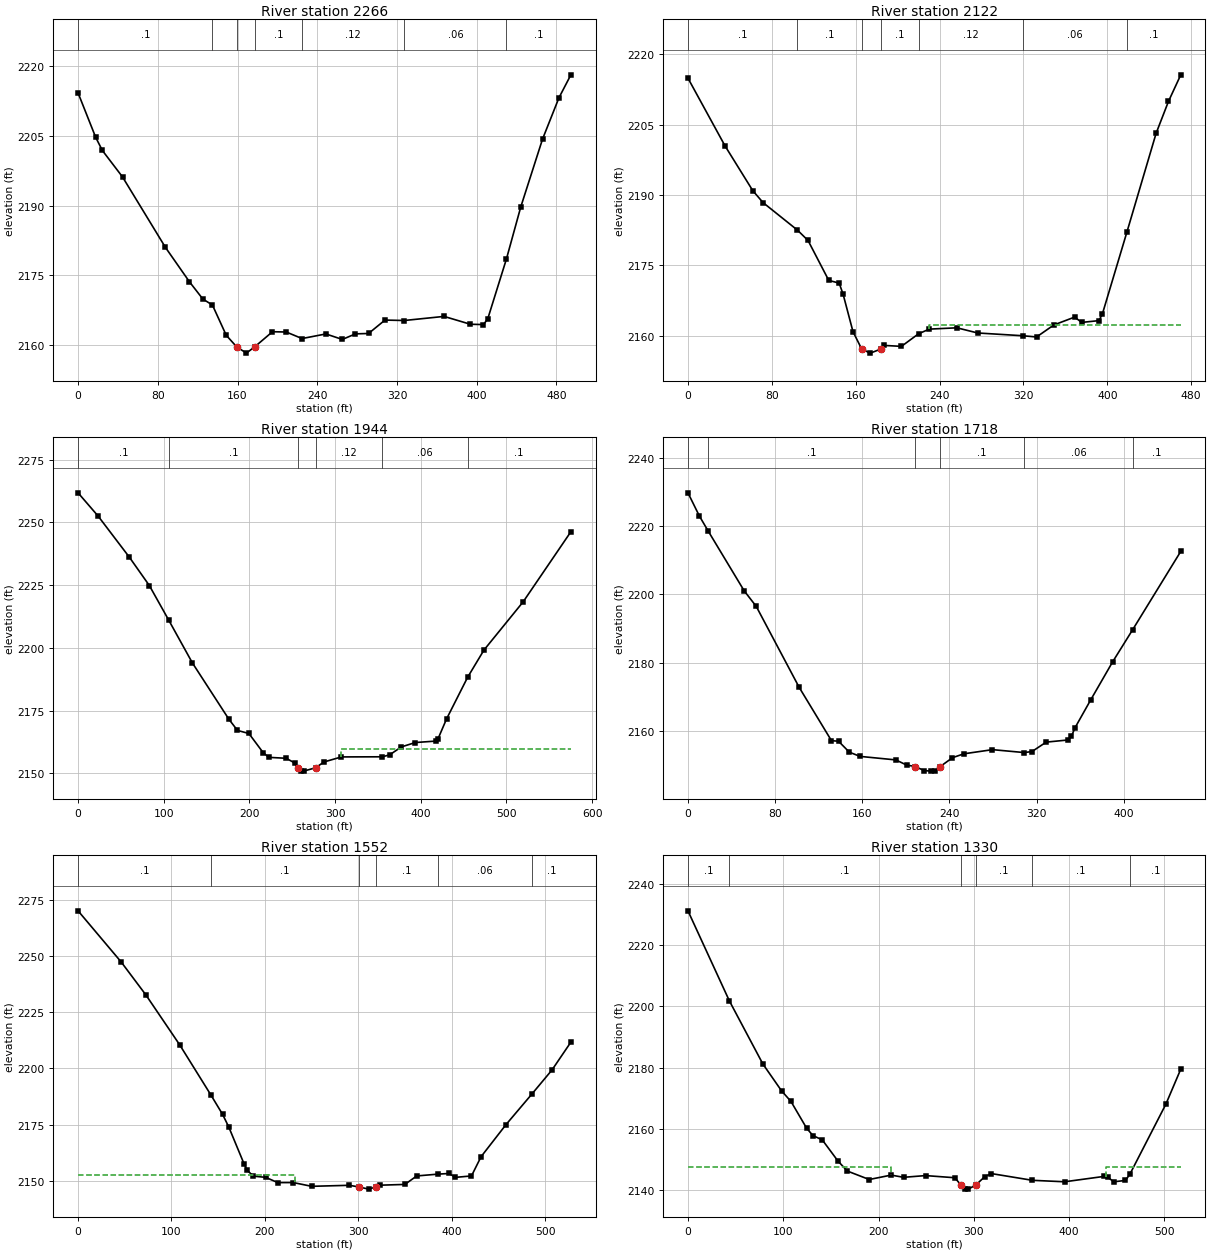
Type RM Length L Ch R = 1 ,2266    ,144,144,144
XS GIS Cut Line= 3
2172366.40392301262927.4873963462172569.81235701262972.175612906
2172854.89235921262998.372153648
#Sta/Elev= 30
       0 2214.29    17.7 2204.71    24.4 2201.88    44.6 2196.19    87.7    2181
   111.8 2173.59   125.2 2169.89  134.862168.581   148.7 2162.08  159.042159.608
   168.9 2158.23  177.412159.609   195.1 2162.84   208.9 2162.78  224.752161.371
   248.7 2162.36   265.2 2161.18   278.4 2162.38   291.5 2162.46     308 2165.35
  327.342165.258   367.3 2166.14   393.7 2164.45   406.8 2164.38   411.1  2165.6
  429.922178.544   444.2 2189.68   466.1 2204.33   482.6 2213.25494.5406 2218.18
#Mann= 7 ,-1 , 0
       0      .1       0  134.86      .1       0  159.04    .045       0
  177.41      .1       0  224.75     .12       0  327.34     .06       0
  429.92      .1       0
#XS Ineff= 2 , 0
                          205.12         2162.19
Permanent Ineff=
       F       F
Bank Sta=159.04,177.41
XS Rating Curve= 0 ,0
Exp/Cntr(USF)=0,0
Exp/Cntr=0.3,0.1

Type RM Length L Ch R = 1 ,2122    ,178.4,178.4,178.4
XS GIS Cut Line= 3
 2172387.9775448 263123.190965422172625.28738447263096.994424678
2172854.89235921263069.256910951
#Sta/Elev= 30
       0 2214.87    35.3 2200.47    61.8 2190.93    71.6 2188.38  104.422182.519
   114.5 2180.32   134.3 2171.81   144.2 2171.24     148 2168.85   157.4  2160.9
  165.75 2157.18   173.9 2156.33  183.75 2157.18   187.1 2157.97   203.6 2157.77
  219.932160.446   230.1 2161.44   256.5 2161.72   276.3 2160.62  319.35 2160.03
   332.5 2159.77     349 2162.33   368.8    2164   375.5 2162.87     392 2163.25
   395.3  2164.7  418.762182.185   446.5 2203.13   458.3 2209.93470.0257 2215.58
#Mann= 7 ,-1 , 0
       0      .1       0  104.42      .1       0  165.75    .045       0
  183.75      .1       0  219.93     .12       0  319.35     .06       0
  418.76      .1       0
#XS Ineff= 2 , 0
                          229.87          2162.3
Permanent Ineff=
       F       F
Bank Sta=165.75,183.75
XS Rating Curve= 0 ,0
Exp/Cntr(USF)=0,0
Exp/Cntr=0.3,0.1

Type RM Length L Ch R = 1 ,1944    ,225.5,225.5,225.5
XS GIS Cut Line= 4
2172380.27267988263300.4028586772172597.54987074 263266.50145301
2172686.92630386263243.386858238 2172947.3507383263206.403506602
#Sta/Elev= 30
       0 2261.77    23.4 2252.51    59.9 2236.11    83.2 2224.83  105.722211.107
   133.5 2193.96   176.1 2171.52   186.1 2167.08   199.4 2165.86   216.1 2158.22
   222.7 2156.35     243 2155.98   253.2 2154.04  257.22 2152.19     260 2150.97
   263.3 2150.86  277.172152.188   287.1 2154.51   307.4 2156.52  355.362156.575
   363.8 2157.36   377.3  2160.5   393.7 2162.26   417.6 2162.83   420.2 2163.75
   430.1 2171.63  454.712188.241   473.8 2199.11   519.6 2218.35575.2604 2246.26
#Mann= 6 ,-1 , 0
       0      .1       0  105.72      .1       0  257.22    .045       0
  277.17     .12       0  355.36     .06       0  454.71      .1       0
#XS Ineff= 2 , 0
                          307.01         2159.86
Permanent Ineff=
       F       F
Bank Sta=257.22,277.17
XS Rating Curve= 0 ,0
Exp/Cntr(USF)=0,0
Exp/Cntr=0.3,0.1

Type RM Length L Ch R = 1 ,1718    ,166.2,166.2,166.2
XS GIS Cut Line= 3
 2172458.8623021  263460.66404912172708.49992565263471.450859994
2172910.36738666263456.041130146
#Sta/Elev= 30
       0 2229.68    10.5 2222.89   18.63 2218.47    51.6 2201.03    62.7 2196.46
   102.1 2172.79   131.7 2157.22   138.2 2157.05   148.1 2153.86   157.9 2152.62
   190.8 2151.59   200.6  2150.1  208.312149.659     217 2148.46   223.3 2148.31
   226.9 2148.41  231.59 2149.66   242.8 2152.24   253.2 2153.37   279.5 2154.59
  308.442153.745   315.7 2154.02   328.8 2156.79   348.6 2157.41   351.9 2158.44
   355.2 2160.96   369.8 2169.22   389.7 2180.22  408.132189.646452.3253 2212.56
#Mann= 6 ,-1 , 0
       0      .1       0   18.63      .1       0  208.31    .045       0
  231.59      .1       0  308.44     .06       0  408.13      .1       0
Bank Sta=208.31,231.59
XS Rating Curve= 0 ,0
Exp/Cntr(USF)=0,0
Exp/Cntr=0.3,0.1

Type RM Length L Ch R = 1 ,1552    ,221.8,221.8,221.8
XS GIS Cut Line= 4
2172409.55116659263653.2856722052172682.30338491263639.416915341
2172841.02360234263588.5648068422172928.85906248263587.023833857
#Sta/Elev= 30
       0 2270.12    46.2 2247.34    72.7 2232.64   108.8 2210.49  142.242188.147
   154.8 2179.49   161.4 2173.87   177.8 2157.43   181.1 2154.65   187.6 2152.05
   200.8  2151.5   213.9 2149.16   230.4 2149.18   250.1 2147.51   290.3 2147.96
  300.782147.242     311 2146.26  318.952147.242   323.8 2148.02   349.9 2148.35
   362.6 2152.13  385.472152.935   397.1 2153.22     404  2151.5   421.2 2152.13
   431.5 2160.71   458.2 2174.99  485.882188.575   507.4 2199.29 527.621 2211.68
#Mann= 6 ,-1 , 0
       0      .1       0  142.24      .1       0  300.78    .045       0
  318.95      .1       0  385.47     .06       0  485.88      .1       0
#XS Ineff= 2 , 0
          232.73 2152.61
Permanent Ineff=
       F       F
Bank Sta=300.78,318.95
XS Rating Curve= 0 ,0
Exp/Cntr(USF)=0,0
Exp/Cntr=0.3,0.1

Type RM Length L Ch R = 1 ,1330    ,199.7,199.7,199.7
XS GIS Cut Line= 4
2172475.81300494263813.5468626282172736.23743938263824.333673522
2172847.18749428263865.9399441132172979.71117098263827.415619492
#Sta/Elev= 30
       0 2231.17   43.522201.729    78.6 2181.17    98.3 2172.36   108.1 2168.93
   124.5 2160.21   131.1  2157.8     141 2156.36   157.4 2149.48   167.2 2146.21
   190.2 2143.44   213.2 2144.88   226.3 2144.16   249.3 2144.72   280.1 2144.02
  286.552141.597   290.6 2140.37   294.1  2140.3  301.932141.601   311.6 2144.41
   318.5 2145.37  361.442143.177   395.3  2142.7   436.3 2144.44   440.6 2144.24
   446.6 2142.69   459.1 2143.14  463.742145.169   501.5 2168.03 517.152 2179.49
#Mann= 6 ,-1 , 0
       0      .1       0   43.52      .1       0  286.55    .045       0
  301.93      .1       0  361.44      .1       0  463.74      .1       0
#XS Ineff= 2 , 0
          213.17 2147.53  438.96         2147.43
Permanent Ineff=
       F       F
Bank Sta=286.55,301.93
XS Rating Curve= 0 ,0
Exp/Cntr(USF)=0,0
Exp/Cntr=0.3,0.1

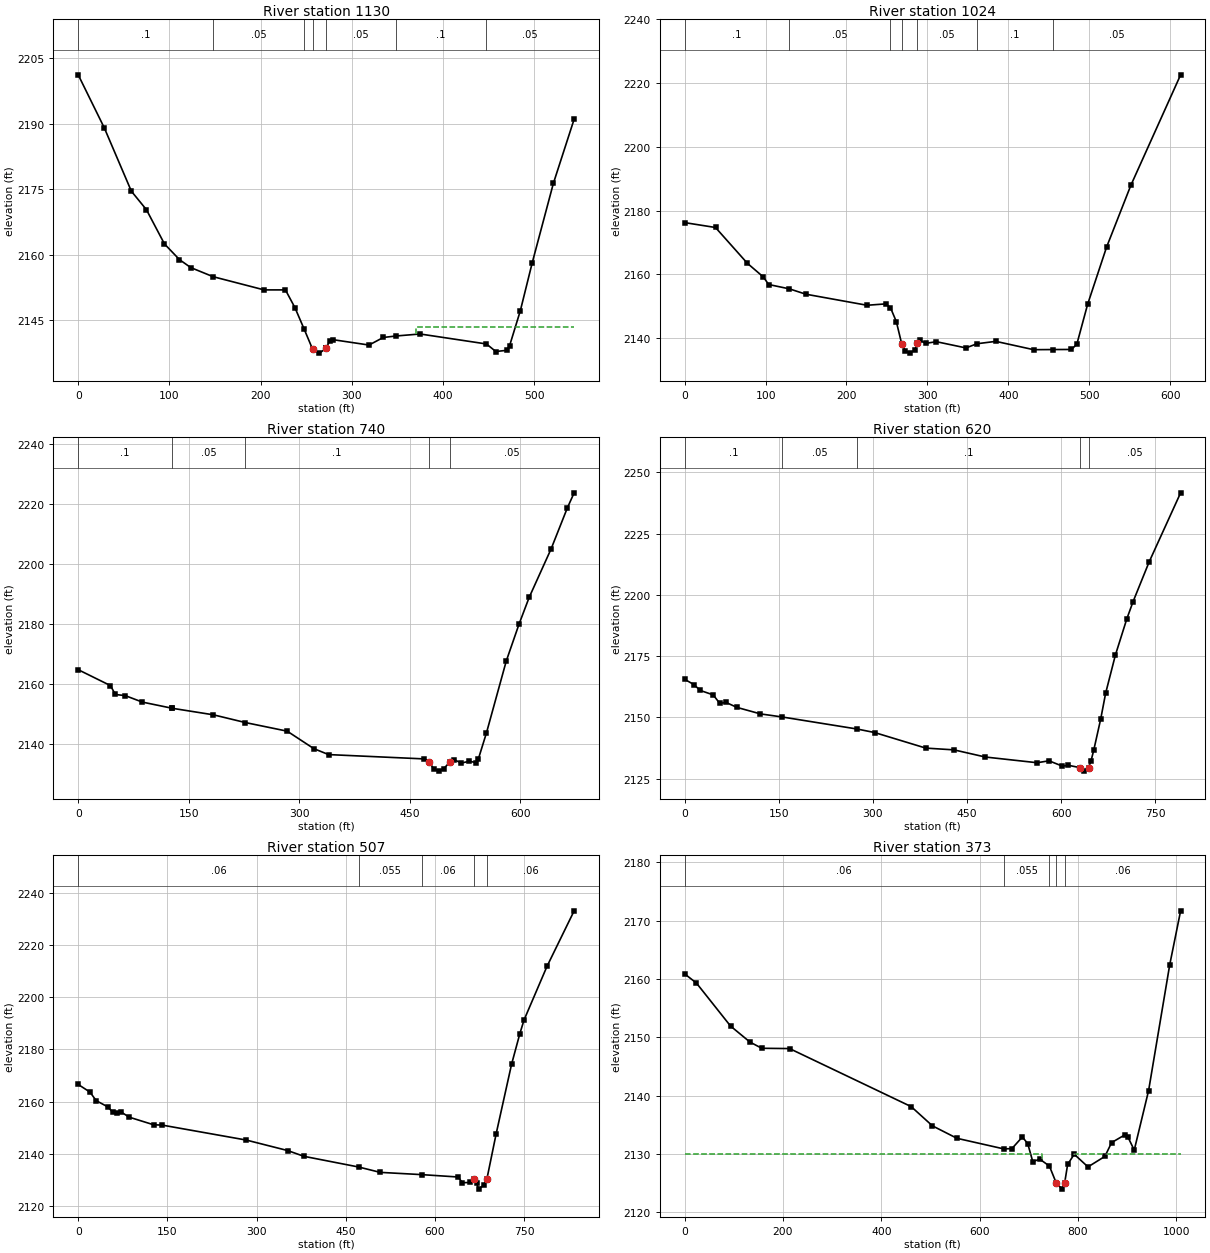
Type RM Length L Ch R = 1 ,1130    ,106.5,106.5,106.5
XS GIS Cut Line= 4
2172512.79635657264064.7254591572172725.45062848  264040.0698914
2172856.43333219263996.9226478242173045.97300933263966.103188127
#Sta/Elev= 30
       0 2201.17    28.6 2189.04    58.3 2174.54    74.8 2170.32    94.6 2162.48
   111.1 2158.88   123.5 2157.06  148.042154.977   203.9 2151.96   227.3 2151.96
   237.7 2147.91  247.862142.976  257.122138.382   264.5 2137.49   272.2  2138.6
   272.2 2138.62   275.7 2140.33   279.1 2140.58     319 2139.34   334.6 2141.07
  348.432141.408     375 2141.87   447.82139.587   458.1 2137.86   470.1 2138.13
   473.1 2139.12     485 2147.21   497.9 2158.07   521.2 2176.32544.0141 2191.03
#Mann= 7 ,-1 , 0
       0      .1       0  148.04     .05       0  247.86      .1       0
  257.12    .045       0   272.2     .05       0  348.43      .1       0
   447.8     .05       0
#XS Ineff= 2 , 0
                          370.91         2143.51
Permanent Ineff=
       F       F
Bank Sta=257.12,272.2
XS Rating Curve= 0 ,0
Exp/Cntr(USF)=0,0
Exp/Cntr=0.3,0.1

Type RM Length L Ch R = 1 ,1024    ,284.4,284.4,284.4
XS GIS Cut Line= 3
 2172519.6051751264145.5504341752172814.17161136264126.748321222
2173126.64482187264068.551304939
#Sta/Elev= 30
       0 2176.21    38.1 2174.68    77.5 2163.45    97.2 2159.17   103.8  2156.8
   129.5 2155.43   149.8 2153.76   225.4 2150.29   248.5 2150.72   254.3 2149.57
   261.6 2145.17   268.2 2138.24   272.8 2135.99     278 2135.28   284.6 2136.26
   287.5 2138.51   291.2 2139.28   297.8 2138.35   311.2 2138.86   347.7 2136.91
   361.2 2138.22   384.6 2138.97   431.3 2136.36   454.9  2136.4     478 2136.43
   484.7 2138.06     498 2150.54   521.4 2168.47   551.4 2187.86     613 2222.56
#Mann= 7 ,-1 , 0
       0      .1       0   129.5     .05       0   254.3      .1       0
   268.2    .045       0   287.5     .05       0   361.2      .1       0
   454.9     .05       0
Bank Sta=268.2,287.5
XS Rating Curve= 0 ,0
Exp/Cntr(USF)=0,0
Exp/Cntr=0.3,0.1

Type RM Length L Ch R = 1 ,740     ,119.9,119.9,119.9
XS GIS Cut Line= 4
2172563.61927762 264204.064755132173020.38021229264280.970554215
2173024.57620869264236.8749828032173172.08251294264161.276518081
#Sta/Elev= 30
       0 2164.67    43.8 2159.37    50.4 2156.41    63.8 2156.04      87 2153.88
     127 2151.85     127 2151.84   183.5 2149.64   226.9 2147.06   283.7 2144.19
   319.9 2138.36   339.9 2136.39   469.7 2134.95   476.3 2134.05   482.9 2131.49
   489.5 2130.88   496.1 2131.68   505.1 2134.08   509.9 2134.71   520.2 2133.59
     531 2134.16   539.7 2133.74   543.1 2134.87   554.2 2143.65   581.1  2167.6
   598.4 2179.86   612.1 2188.73   642.1 2205.02     664 2218.59   673.2 2223.59
#Mann= 5 ,-1 , 0
       0      .1       0     127     .05       0   226.9      .1       0
   476.3    .045       0   505.1     .05       0
Bank Sta=476.3,505.1
XS Rating Curve= 0 ,0
Exp/Cntr(USF)=0,0
Exp/Cntr=0.5,0.3

Type RM Length L Ch R = 1 ,620     ,112.8,112.8,112.8
XS GIS Cut Line= 4
2172559.95068075264207.0506027442173085.11806369264364.491435746
2173162.00215828264244.7404224892173252.88276943264203.462587654
#Sta/Elev= 30
       0 2165.52    14.7 2163.37    24.9 2160.97    45.5 2159.16    55.8 2155.72
      66 2156.08    83.2 2154.06   120.8  2151.4     155 2150.16     275 2145.22
   302.6  2143.8   384.3 2137.44   429.2 2136.72   479.1  2133.8   561.7 2131.47
   580.7 2132.25     602 2130.07   611.5 2130.42   630.5 2129.44   635.8 2128.04
   643.6 2129.52   647.5 2132.11   651.9 2136.55   663.1 2149.39   670.9 2159.85
   686.4 2175.38   704.7 2190.24   714.6 2197.22   740.2 2213.43   790.4 2241.65
#Mann= 5 ,-1 , 0
       0      .1       0     155     .05       0     275      .1       0
   630.5    .045       0   643.6     .05       0
Bank Sta=630.5,643.6
XS Rating Curve= 0 ,0
Exp/Cntr(USF)=0,0
Exp/Cntr=0.5,0.3

Type RM Length L Ch R = 1 ,507     ,134.2,134.2,134.2
XS GIS Cut Line= 4
2172555.23637314264208.1483636512173134.44920994264402.230151898
2173231.49010407264371.9048724842173345.20990187264329.449481305
#Sta/Elev= 30
       0 2166.54    19.8 2163.61    30.2 2160.35    50.9 2157.81    57.8 2155.86
    64.8 2155.46    71.7 2156.08    85.5 2154.03     127 2151.09   140.9 2150.99
   282.8 2145.24     352 2141.24   379.6 2139.02   471.5 2134.93   507.7 2132.88
   577.8 2132.01     639  2131.1   645.8 2128.92   659.6 2129.01   666.2  2130.2
   669.9 2128.76   673.3 2126.46   681.9 2128.02     687 2130.15   702.8  2147.7
   728.6 2174.21   742.6 2186.01   749.6 2191.21   788.2 2211.74   833.9 2233.03
#Mann= 5 ,-1 , 0
       0     .06       0   471.5    .055       0   577.8     .06       0
   666.2    .045       0     687     .06       0
Bank Sta=666.2,687
XS Rating Curve= 0 ,0
Exp/Cntr(USF)=0,0
Exp/Cntr=0.3,0.1

Type RM Length L Ch R = 1 ,373     ,70.6,70.6,70.6
XS GIS Cut Line= 4
2172546.41568503264218.5267292382173219.05039292264487.580612391
2173341.09545332264533.347510041 2173495.0386545264538.895012786
#Sta/Elev= 30
       0 2160.85    23.9 2159.28    93.3 2151.91   132.9 2149.16   156.9  2148.1
   213.4 2148.05   460.8  2138.1   503.9 2134.81   553.9 2132.67  649.322130.851
   665.7 2130.91   686.9  2132.9   697.8 2131.76   708.1 2128.67   722.3  2129.1
  741.872127.918  755.962124.985   767.8 2123.96   772.92124.985     779 2128.19
   792.4 2129.94   820.4 2127.77   854.8 2129.57   868.5 2131.94   894.8 2133.23
   901.4 2132.93   914.5 2130.65   943.7 2140.85   986.7 2162.431008.837 2171.66
#Mann= 5 ,-1 , 0
       0     .06       0  649.32    .055       0  741.87     .06       0
  755.96    .045       0   772.9     .06       0
#XS Ineff= 2 , 0
          726.39 2130.01  791.02         2129.96
Permanent Ineff=
       F       F
Bank Sta=755.96,772.9
XS Rating Curve= 0 ,0
Exp/Cntr(USF)=0,0
Exp/Cntr=0.5,0.3

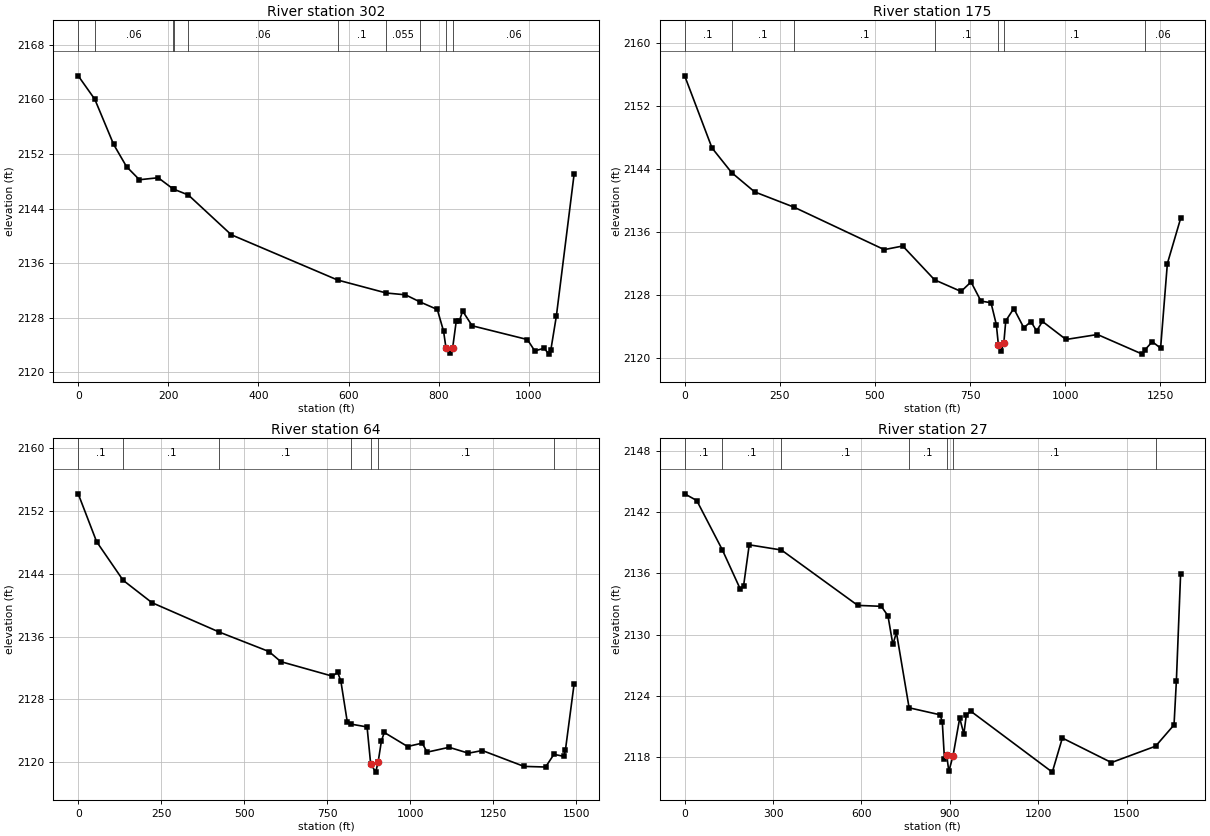
Type RM Length L Ch R = 1 ,302     ,127,127,127
XS GIS Cut Line= 4
2172511.74379288264247.6511186522173202.40788468264547.216266904
 2173424.3079945264633.2025594582173531.09742235264608.238797104
#Sta/Elev= 30
       0 2163.46   36.862160.015    78.6  2153.4   107.2 2150.14   135.8 2148.22
   177.5 2148.51  210.692146.865  211.922146.833  244.332145.985   339.6 2140.15
  575.672133.508  683.662131.605   726.2 2131.34  758.522130.294   796.8 2129.19
   810.7 2126.01  816.032123.562   824.6 2122.74   830.9 2123.58   838.9  2127.5
   845.9 2127.54     853 2128.96   874.1  2126.8   996.7 2124.78  1013.1 2123.11
    1034 2123.51  1044.1 2122.64  1048.6 2123.19    1061 2128.221100.478 2149.08
#Mann= 10 ,-1 , 0
       0      .1       0   36.86     .06       0  210.69      .1       0
  211.92      .1       0  244.33     .06       0  575.67      .1       0
  683.66    .055       0  758.52      .1       0  816.03    .045       0
   830.9     .06       0
Bank Sta=816.03,830.9
XS Rating Curve= 0 ,0
Exp/Cntr(USF)=0,0
Exp/Cntr=0.5,0.3

Type RM Length L Ch R = 1 ,175     ,110.9,110.9,110.9
XS GIS Cut Line= 4
2172497.87503601264287.8705135562173171.89661958264656.779446126
2173395.18360508264780.2113822122173660.07686118264690.064462599
#Sta/Elev= 30
       0 2155.77    71.8 2146.61  123.622143.472   183.9 2141.03  287.41 2139.09
   524.4  2133.7   573.1 2134.16  656.682129.865   726.3 2128.39   752.5 2129.59
   778.7 2127.16     805 2126.96     819 2124.18   824.4 2121.64   831.2 2120.84
   838.7 2121.84   843.8 2124.66   864.9 2126.22   891.2 2123.78   909.9 2124.56
   924.9 2123.38   940.3 2124.58  1002.1 2122.29  1084.8 2122.92  1202.7 2120.43
 1209.352120.958  1228.8 2122.01  1250.7 2121.19  1268.5 2131.931303.319 2137.66
#Mann= 7 ,-1 , 0
       0      .1       0  123.62      .1       0  287.41      .1       0
  656.68      .1       0   824.4    .045       0   838.7      .1       0
 1209.35     .06       0
Bank Sta=824.4,838.7
XS Rating Curve= 0 ,0
Exp/Cntr(USF)=0,0
Exp/Cntr=0.3,0.1

Type RM Length L Ch R = 1 ,64      ,37.4,37.4,37.4
XS GIS Cut Line= 4
2172449.33438699264289.2573892422173133.06410036264762.181998289
2173435.40299999264916.1251994752173675.33249373264699.772592403
#Sta/Elev= 30
       0 2154.16    55.4 2148.07  135.162143.159     222 2140.31  425.392136.555
   574.4 2134.09   610.3  2132.8   765.2 2130.96   781.7 2131.43   791.1 2130.31
   810.2 2125.18  822.922124.841     870 2124.49   880.82119.806   896.1 2118.74
   903.5 2120.08   913.3 2122.73   921.9 2123.79   991.9    2122  1036.1 2122.43
  1050.7 2121.28    1117  2121.9  1175.3 2121.15  1217.1 2121.49  1342.6 2119.47
  1407.6 2119.39  1432.82121.004  1462.5 2120.75  1467.4 2121.551493.696 2130.01
#Mann= 7 ,-1 , 0
       0      .1       0  135.16      .1       0  425.39      .1       0
  822.92      .1       0   880.8    .045       0   903.5      .1       0
  1432.8     .06       0
Bank Sta=880.8,903.5
XS Rating Curve= 0 ,0
Exp/Cntr(USF)=0,0
Exp/Cntr=0.3,0.1

Type RM Length L Ch R = 1 ,27      ,27,27,27
XS GIS Cut Line= 6
 2172418.3242511264373.8857960432173049.88224711264748.175471184
2173162.47108261264814.4631552732173238.01149332264853.535781504
2173490.02993251264982.475448065 2173844.9119287264704.895832974
#Sta/Elev= 30
       0 2143.82      41 2143.16   127.6 2138.33   188.6 2134.47     200 2134.79
   219.1 2138.81   328.4  2138.3   587.5 2132.86   667.3 2132.77     690 2131.84
   706.7 2129.02   718.8  2130.2   761.8  2122.8   867.3 2122.11   874.5  2121.4
   881.8 2117.77   889.3 2118.17   896.7 2116.55  911.04  2118.1   933.6 2121.79
   947.7 2120.23   955.8 2122.06   970.5 2122.48  1247.9 2116.48    1282 2119.83
  1448.6 2117.42  1598.6 2119.03  1661.1 2121.12    1669 2125.391683.472 2135.98
#Mann= 7 ,-1 , 0
       0      .1       0   127.6      .1       0   328.4      .1       0
   761.8      .1       0   889.3    .045       0  911.04      .1       0
  1598.6     .06       0
Bank Sta=889.3,911.04
XS Rating Curve= 0 ,0
Exp/Cntr(USF)=0,0
Exp/Cntr=0.3,0.1
Stream Node=BIGCLEARCK      ,Main            , 0 , 0 ,Upstream end
Stream Node=BIGCLEARCK      ,Main            , 0 , 1 ,Downstream end
Stream Node=BROADRN         ,Main            , 0 , 0 ,Upstream end
Stream Node=BROADRN         ,Main            , 0 , 1 ,Downstream end
Stream Node=LAURELBR        ,Main            , 0 , 0 ,Upstream end
Stream Node=LAURELBR        ,Main            , 0 , 1 ,Downstream end
Stream Node=LAURELCK1       ,Main            , 0 , 0 ,Upstream end
Stream Node=LAURELCK1       ,Main            , 0 , 1 ,Downstream end
Stream Node=MEADOWRV3       ,Main            , 0 , 0 ,Upstream end
Stream Node=MEADOWRV3       ,Main            , 0 , 1 ,Downstream end
Stream Node=MEADOWRV4       ,Main            , 0 , 0 ,Upstream end
Stream Node=MEADOWRV4       ,Main            , 0 , 1 ,Downstream end
Stream Node=MLGNCK          ,Main            , 0 , 0 ,Upstream end
Stream Node=MLGNCK          ,Main            , 0 , 1 ,Downstream end
Stream Node=MLGNCKTR3       ,Main            , 0 , 0 ,Upstream end
Stream Node=MLGNCKTR3       ,Main            , 0 , 1 ,Downstream end
Stream Node=MLGNCKTR4       ,Main            , 0 , 0 ,Upstream end
Stream Node=MLGNCKTR4       ,Main            , 0 , 1 ,Downstream end
Stream Node=MUDDYCK         ,Main            , 0 , 0 ,Upstream end
Stream Node=MUDDYCK         ,Main            , 0 , 1 ,Downstream end
Stream Node=SECONDCK        ,Main            , 0 , 0 ,Upstream end
Stream Node=SECONDCK        ,Main            , 0 , 1 ,Downstream end
Stream Node=TUCKHORN        ,Main            , 0 , 0 ,Upstream end
Stream Node=TUCKHORN        ,Main            , 0 , 1 ,Downstream end
Stream Node=TUCKHORNT2      ,Main            , 0 , 0 ,Upstream end
Stream Node=TUCKHORNT2      ,Main            , 0 , 1 ,Downstream end
LCMann Table=0

Chan Stop Cuts=-1
Use User Specified Reach Order=0
Composite Channel Slope=5